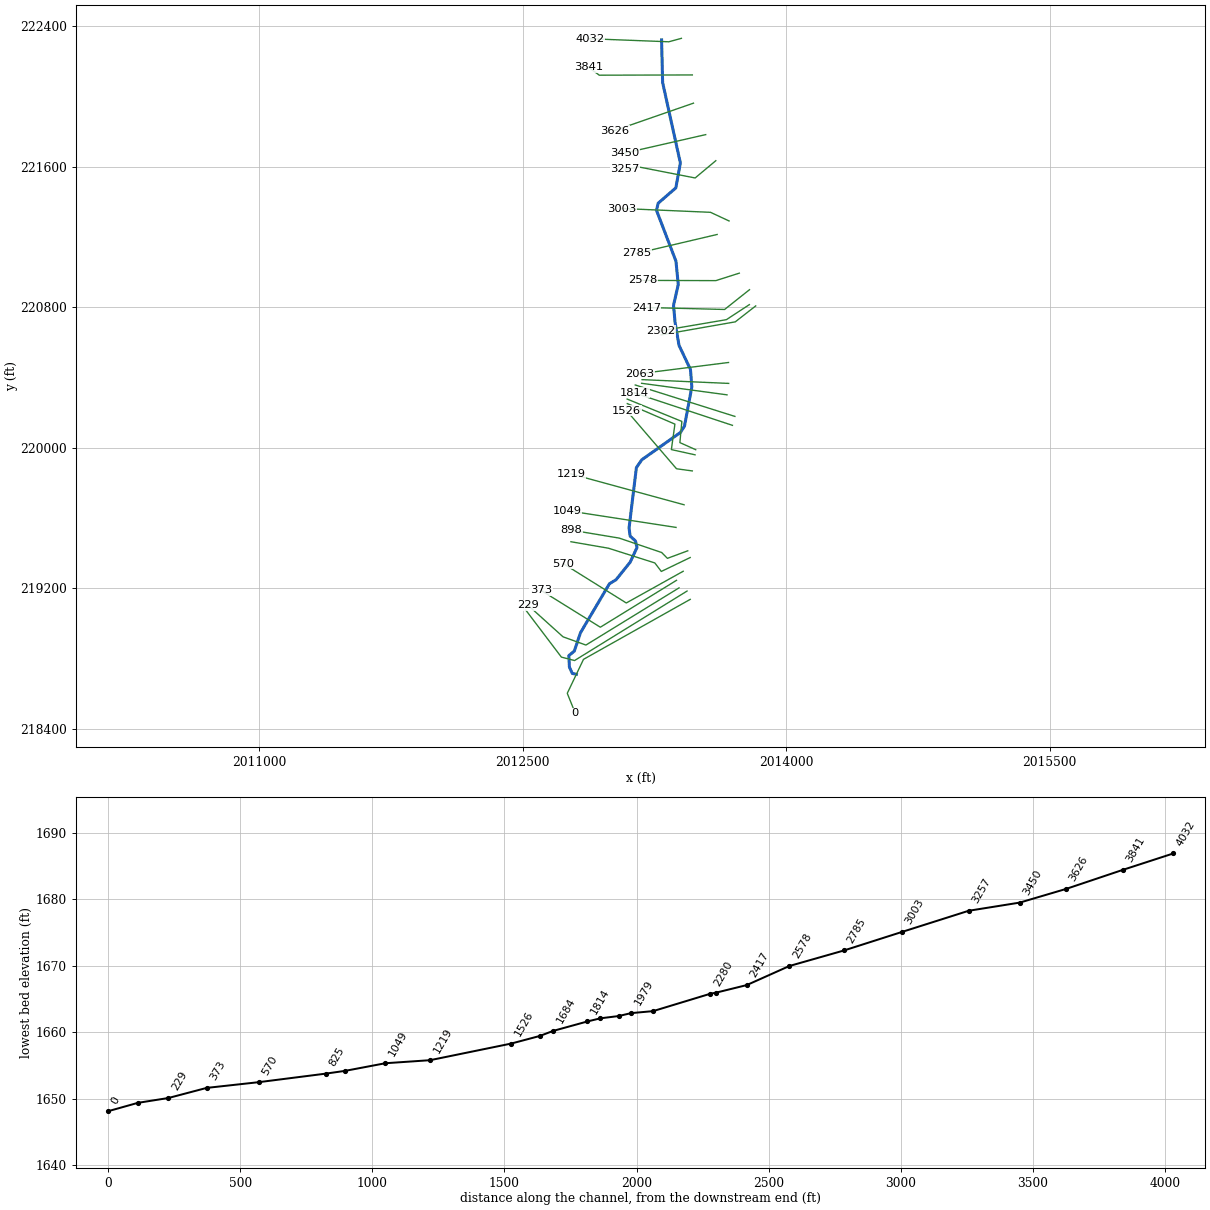
--- WOLFCK_T1.prj (project) ---

Proj Title=WOLFCK_T1
Current Plan=p01
Default Exp/Contr=0,0
English Units
Geom File=g01
Flow File=f01
Plan File=p01
BEGIN DESCRIPTION:
Stream Name: Wolf Creek Tributary 1
Flood Zone: Approximate
Summers County, West Virginia
HEC-RAS Version: 5.0.7
Hydrology Method:
regression
Model Notes:
coincident peak with WOLDCK_A, KWSEL tie-in/shared XS with WOLFCK_A
END DESCRIPTION:
DSS Export Rating Curves= 0
DSS Export Rating Curve Sorted= 0
DSS Export Volume Flow Curves= 0
DXF OffsetX= 0
DXF OffsetY= 0
DXF ScaleX= 0
DXF ScaleY= 0

--- WOLFCK_T1.p01 (plan) ---

Plan Title=Floodplain
Program Version=5.07
Short Identifier=Floodplain
Geom File=g01
Flow File=f01
Subcritical Flow
K Sum by GR= 0
Std Step Tol= 0.01
Critical Tol= 0.01
Num of Std Step Trials= 20
Max Error Tol= 0.3
Flow Tol Ratio= 0.001
Split Flow NTrial= 30
Split Flow Tol= 0.02
Split Flow Ratio= 0.02
Log Output Level= 0
Friction Slope Method= 1
Unsteady Friction Slope Method= 2
Unsteady Bridges Friction Slope Method= 1
Parabolic Critical Depth
Global Vel Dist= 0 , 0 , 0
Global Log Level= 0
CheckData=True
Encroach Param=-1 ,0,0, 0
Mapping Interval=1HOUR
Computation Time Step Use Courant=        0
Computation Time Step Use Time Series=    0
Computation Time Step Count To Double=0
Computation Time Step Max Doubling=0
Computation Time Step Max Halving=0
Computation Time Step Residence Courant=0
Run HTab= 0
Run UNet= 0
Run Sediment= 0
Run PostProcess= 0
Run WQNet= 0
Run RASMapper= 0
UNET Theta= 0
UNET Theta Warmup= 0
UNET ZTol= 0
UNET ZSATol= 0
UNET MxIter= 0
UNET Max Iter WO Improvement= 0
UNET MaxInSteps= 0
UNET DtIC= 0
UNET DtMin= 0
UNET MaxCRTS= 0
UNET WFStab= 0
UNET SFStab= 0
UNET WFX= 1
UNET SFX= 1
UNET 1D Methodology=Finite Difference
UNET DSS MLevel= 1
UNET Pardiso=0
UNET DZMax Abort= 0
UNET Use Existing IB Tables= 0
UNET Froude Reduction=False
UNET Froude Limit= 0
UNET Froude Power= 0
UNET D1 Cores= 0
UNET D2 Coriolis=0
UNET D2 Cores= 0
UNET D2 Theta= 1
UNET D2 Theta Warmup= 1
UNET D2 Z Tol= 0.01
UNET D2 Volume Tol= 0.01
UNET D2 Max Iterations= 20
UNET D2 Equation= 0
UNET D2 RampUpFraction=0.1
UNET D2 TimeSlices= 1
UNET D2 BCVolumeCheck=0
UNET D1D2 MaxIter= 0
UNET D1D2 ZTol=0.01
UNET D1D2 QTol=0.1
UNET D1D2 MinQTol=1
Write IC File= 0
Write IC File at Fixed DateTime=0
Write IC File at Sim End=0
Echo Input=False
Echo Parameters=False
Echo Output=False
Write Detailed= 0
HDF Write Warmup=0
HDF Write Time Slices=0
HDF Flush=0
HDF Face Node Velocities=0
HDF Compression= 1
HDF Chunk Size= 1
HDF Spatial Parts= 1
HDF Use Max Rows=0
HDF Fixed Rows= 1
Calibration Method= 0
Calibration Iterations= 20
Calibration Max Change=0.05
Calibration Tolerance=0.2
Calibration Maximum=1.5
Calibration Minimum=0.5
Calibration Optimization Method= 1
WQ AD Non Conservative
WQ ULTIMATE=-1
WQ Max Comp Step=1HOUR
WQ Output Interval=15MIN
WQ Output Selected Increments= 0
WQ Output face flow=0
WQ Output face velocity=0
WQ Output face area=0
WQ Output face dispersion=0
WQ Output cell volume=0
WQ Output cell surface area=0
WQ Output cell continuity=0
WQ Output cumulative cell continuity=0
WQ Output face conc=0
WQ Output face dconc_dx=0
WQ Output face courant=0
WQ Output face peclet=0
WQ Output face adv mass=0
WQ Output face disp mass=0
WQ Output cell mass=0
WQ Output cell source sink temp=0
WQ Output nsm pathways=0
WQ Output nsm derived pathways=0
WQ Output MaxMinRange=-1
WQ Daily Max Min Mean=-1
WQ Daily Range=0
WQ Daily Time=0
WQ Create Restart=0
WQ Fixed Restart=0
WQ System Summary=0
WQ Write To DSS=0
WQ Use Fixed Temperature=0
Sorting and Armoring Iterations= 10
XS Update Threshold= 0.02
Bed Roughness Predictor= 0
Hydraulics Update Threshold= 0.02
Energy Slope Method= 1
Volume Change Method= 1
Sediment Retention Method= 0
XS Weighting Method= 0
Number of US Weighted Cross Sections= 1
Number of DS Weighted Cross Sections= 1
Upstream XS Weight=0
Main XS Weight=1
Downstream XS Weight=0
Number of DS XS's Weighted with US Boundary= 1
Upstream Boundary Weight= 1
Weight of XSs Associated with US Boundary= 0
Number of US XS's Weighted with DS Boundary= 1
Downstream Boundary Weight= 0.5
Weight of XSs Associated with DS Boundary= 0.5
Percentile Method= 0
Sediment Output Level= 3
Mass or Volume Output= 0
Output Increment Type= 1
Profile and TS Output Increment= 1
XS Output Flag= 0
XS Output Increment= 10
Write Gradation File= 0
Read Gradation Hotstart= 0
Write HDF5 File= 1
Write Binary Output= 1
Write DSS Sediment File= 0
SV Curve= 0
Specific Gage Flag= 0

--- WOLFCK_T1.f01 (steady flow) ---

Flow Title=Flows
Program Version=5.07
Number of Profiles= 6
Profile Names=01pct,10pct,04pct,02pct,0_2pct,01plus
River Rch & RM=WOLFCK_T1,Main            ,4032
     538     284     378     455     753     796
River Rch & RM=WOLFCK_T1,Main            ,3257
     613     325     431     519     855     906
River Rch & RM=WOLFCK_T1,Main            ,0
    1278     697     913    1090    1758    1890
Boundary for River Rch & Prof#=WOLFCK_T1,Main            , 1
Up Type= 0
Dn Type= 1
Dn Known WS=1652.3
Boundary for River Rch & Prof#=WOLFCK_T1,Main            , 2
Up Type= 0
Dn Type= 1
Dn Known WS=1651.8
Boundary for River Rch & Prof#=WOLFCK_T1,Main            , 3
Up Type= 0
Dn Type= 1
Dn Known WS=1652
Boundary for River Rch & Prof#=WOLFCK_T1,Main            , 4
Up Type= 0
Dn Type= 1
Dn Known WS=1652.2
Boundary for River Rch & Prof#=WOLFCK_T1,Main            , 5
Up Type= 0
Dn Type= 1
Dn Known WS=1652.8
Boundary for River Rch & Prof#=WOLFCK_T1,Main            , 6
Up Type= 0
Dn Type= 1
Dn Known WS=1652.9
DSS Import GetInterval= 0
DSS Import GetPeak= 0
DSS Import FillOption= 0

--- WOLFCK_T1.g01 (geometry) ---

Geom Title=Geometry
Program Version=5.07

River Reach=WOLFCK_T1       ,Main
Reach XY= 30
2013290.61699999222320.620999913     2013296.623222077.982999911
2013397.55755136221620.5140017932013371.91810838221478.852332616
2013270.92799999221391.1769999062013261.90099999221350.204999909
2013372.43677568221061.6709961372013385.51199999220928.676999906
     2013358.667 220810.128999912013367.26100188220715.018555049
2013389.67799999220582.843999911     2013454.956220445.343999907
2013462.83022054220346.2732204522013420.81001165220122.236274133
2013398.24722054220086.8356672062013177.81499999219931.078999918
     2013147.259219886.6339999152013105.47755513219542.660440998
2013111.61734642219496.896282044 2013142.0536654219469.093336394
     2013150.731219431.7729999132013111.84299999219348.439999909
 2013031.5874392219248.724446658     2012993.787219225.523999918
2012829.20399999218947.050999917     2012793.787 218842.18999991
2012762.95399999218816.9119999112012766.00899999218751.911999914
2012782.40000013218715.0199996262012805.72483032218710.518810713

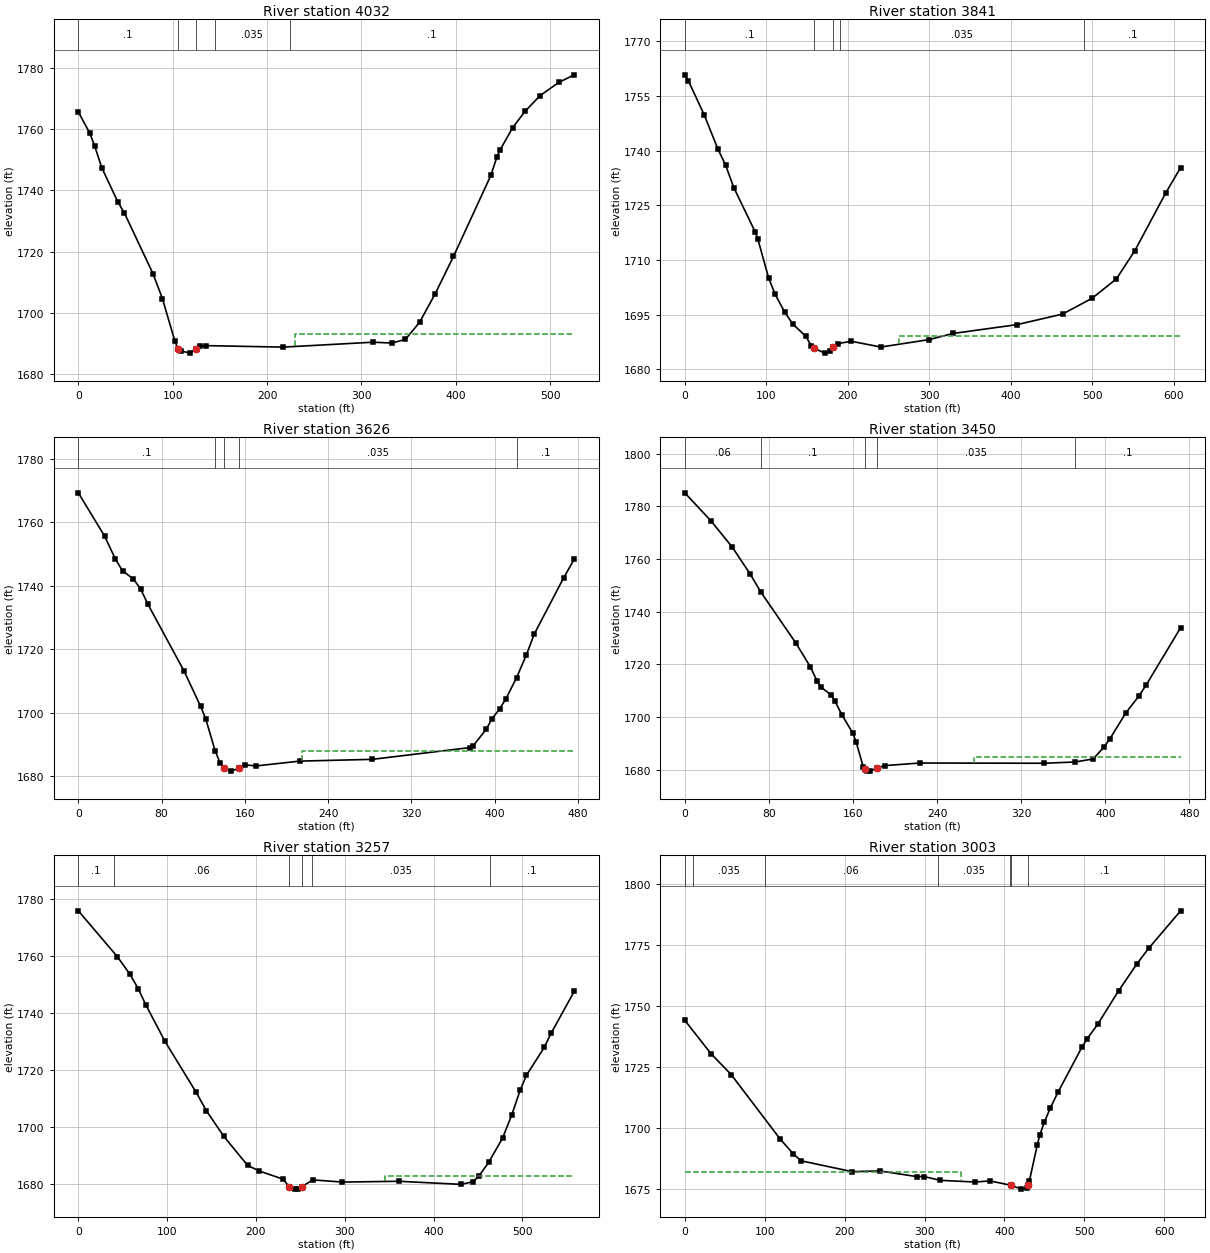
Type RM Length L Ch R = 1 ,4032    ,191.1,191.1,191.1
XS GIS Cut Line= 3
2013403.51055006222329.8017980982013331.71342316222310.149509888
     2012881.054      222327.582
#Sta/Elev= 30
       0 1765.51    12.1 1758.64    17.4 1754.34    24.9 1747.29      42  1736.1
    48.8 1732.58    79.2 1712.73    89.1 1704.66   102.2  1690.9   105.5 1688.33
   108.8 1687.58   118.6 1686.88   125.2 1688.36   128.5 1689.09     135 1689.33
   217.1 1688.84   312.3 1690.44     332 1690.17   346.5 1691.33   361.6 1696.92
     378 1706.16   397.5 1718.39   437.1 1744.81   443.6 1750.89   446.9 1753.13
   460.1 1760.33   473.5 1765.78   489.3 1770.85   509.3 1775.18   525.4 1777.63
#Mann= 5 ,-1 , 0
       0      .1       0   105.5    .045       0   125.2      .1       0
  144.44    .035       0  224.44      .1       0
#XS Ineff= 2 , 0
                             230            1693
Permanent Ineff=
       F       F
Bank Sta=105.5,125.2
XS Rating Curve= 0 ,0
Exp/Cntr=0.3,0.1

Type RM Length L Ch R = 1 ,3841    ,209.2,214.9,218.9
XS GIS Cut Line= 3
2013465.74584005222121.4432019022012936.14793145222120.053710151
2012872.70069379222166.557485458
#Sta/Elev= 30
       0 1760.84     4.3 1759.25      24 1749.75    40.4 1740.57    50.2 1735.96
    60.1 1729.88    86.3 1717.73    89.6 1715.75   102.7 1705.17   110.6 1700.65
   122.4 1695.74   132.2 1692.47   148.6 1688.98   155.2 1686.43   158.5 1685.77
   171.6 1684.41   178.2 1684.98   181.4    1686     188 1687.04   204.4 1687.66
   240.5 1686.08   299.6 1688.12   329.1 1689.81   407.8 1692.24   463.6 1695.15
   499.7 1699.48   529.6 1704.82   552.2 1712.57   590.1 1728.42   608.3 1735.37
#Mann= 5 ,-1 , 0
       0      .1       0   158.5    .045       0   181.4      .1       0
     190    .035       0     490      .1       0
#XS Ineff= 2 , 0
                             263            1689
Permanent Ineff=
       F       F
Bank Sta=158.5,181.4
XS Rating Curve= 0 ,0
Exp/Cntr=0.3,0.1

Type RM Length L Ch R = 1 ,3626    ,176.7,175.5,173.7
XS GIS Cut Line= 2
2013472.12267526221960.8875499492013022.05110508221804.600541076
#Sta/Elev= 30
       0 1769.34    25.2 1755.71    35.6 1748.44    42.5 1744.73      53 1742.13
    59.9 1738.99    66.8 1734.22   101.6  1713.1   117.4 1702.05   122.4 1698.06
   131.4 1687.97   136.3 1684.02   139.8 1682.68   146.7 1681.54   154.6 1682.49
   159.8 1683.51     171 1683.19   212.7  1684.7   282.2 1685.25   375.9 1688.95
   379.4 1689.56   391.8 1694.68   397.4 1698.04   404.7 1701.15   410.7 1704.28
   421.1 1711.04   430.5 1718.23   438.2 1724.88   466.2 1742.47   476.4 1748.36
#Mann= 5 ,-1 , 0
       0      .1       0   131.4    .035       0   139.8    .045       0
   154.6    .035       0   421.1      .1       0
#XS Ineff= 2 , 0
                             215            1688
Permanent Ineff=
       F       F
Bank Sta=139.8,154.6
XS Rating Curve= 0 ,0
Exp/Cntr=0.3,0.1

Type RM Length L Ch R = 1 ,3450    ,198.6,193.4,188.6
XS GIS Cut Line= 2
2013541.69563023221781.7867414552013081.75569737221676.941259073
#Sta/Elev= 30
       0 1785.19    25.1 1774.44    45.3 1764.48    62.1  1754.4    72.2 1747.58
   105.8 1728.05   119.3 1719.17     126 1713.58   129.4 1711.42   139.5 1708.33
   142.9 1706.05   149.6 1700.76   159.7    1694     163 1690.56   169.8 1681.05
   171.3 1680.38   173.1 1679.61   176.5 1679.48   183.2 1680.72     190 1681.57
   223.6 1682.56   341.7 1682.47   371.2 1682.95   388.5  1684.1   398.6 1688.57
   404.5 1691.79   419.7 1701.68   431.9 1707.95     439 1712.24   471.7 1733.96
#Mann= 5 ,-1 , 0
       0     .06       0    72.2      .1       0   171.3    .045       0
   183.2    .035       0   371.2      .1       0
#XS Ineff= 2 , 0
                             275            1685
Permanent Ineff=
       F       F
Bank Sta=171.3,183.2
XS Rating Curve= 0 ,0
Exp/Cntr=0.3,0.1

Type RM Length L Ch R = 1 ,3257    ,245.4,253.6,254.3
XS GIS Cut Line= 4
2013599.27876846221633.3789995022013481.66566934221535.116428536
2013161.08089931221597.7076170462013083.70308886221584.277375218
#Sta/Elev= 30
       0 1775.78    44.1 1759.66      58 1753.61    67.4 1748.53    76.3 1742.65
    97.6 1730.01   132.6 1712.23   144.2 1705.72   163.8 1696.76   190.6 1686.58
   203.9 1684.59   230.7 1681.73   237.4  1679.1     244 1678.25   247.4 1678.25
   251.7 1679.12   264.1 1681.49   297.5 1680.72   360.8    1681   431.2 1679.92
   444.7 1680.86   451.3 1682.93   462.1  1687.6   477.8 1696.17     488 1704.15
   497.6 1712.93   504.7 1718.17   524.7  1727.9   532.3 1732.79   558.4 1747.51
#Mann= 6 ,-1 , 0
       0      .1       0      40     .06       0   237.4    .045       0
   251.7     .06       0  263.26    .035       0  463.26      .1       0
#XS Ineff= 2 , 0
                             345            1683
Permanent Ineff=
       F       F
Bank Sta=237.4,251.7
XS Rating Curve= 0 ,0
Exp/Cntr=0.3,0.1

Type RM Length L Ch R = 1 ,3003    ,211.2,218,220.2
XS GIS Cut Line= 3
2013674.77120354221290.3892045832013569.15070883221339.582311707
2013065.64478886221361.285153085
#Sta/Elev= 30
       0 1744.19    32.6 1730.59      58 1721.99   119.2 1695.62   135.6 1689.55
   145.5 1686.66   209.3 1682.21   243.9 1682.51     290  1680.2   299.8 1680.19
   319.4 1678.66   363.5 1677.96   381.9 1678.42   408.2 1676.63   421.3 1675.05
   427.9  1675.5   429.4 1676.84   431.2 1678.33     441 1693.02   444.3 1697.29
     450 1702.55   457.5 1708.33   467.3 1714.92   496.9 1733.12   503.4 1736.59
   516.6 1742.49   542.8 1756.25   565.8 1767.32   580.4 1773.64   620.5 1789.04
#Mann= 7 ,-1 , 0
       0      .1       0      10    .035       0     100     .06       0
  316.51    .035       0  406.51      .1       0   408.2    .045       0
   429.4      .1       0
#XS Ineff= 2 , 0
             346    1682
Permanent Ineff=
       F       F
Bank Sta=408.2,429.4
XS Rating Curve= 0 ,0
Exp/Cntr(USF)=0,0
Exp/Cntr=0.3,0.1

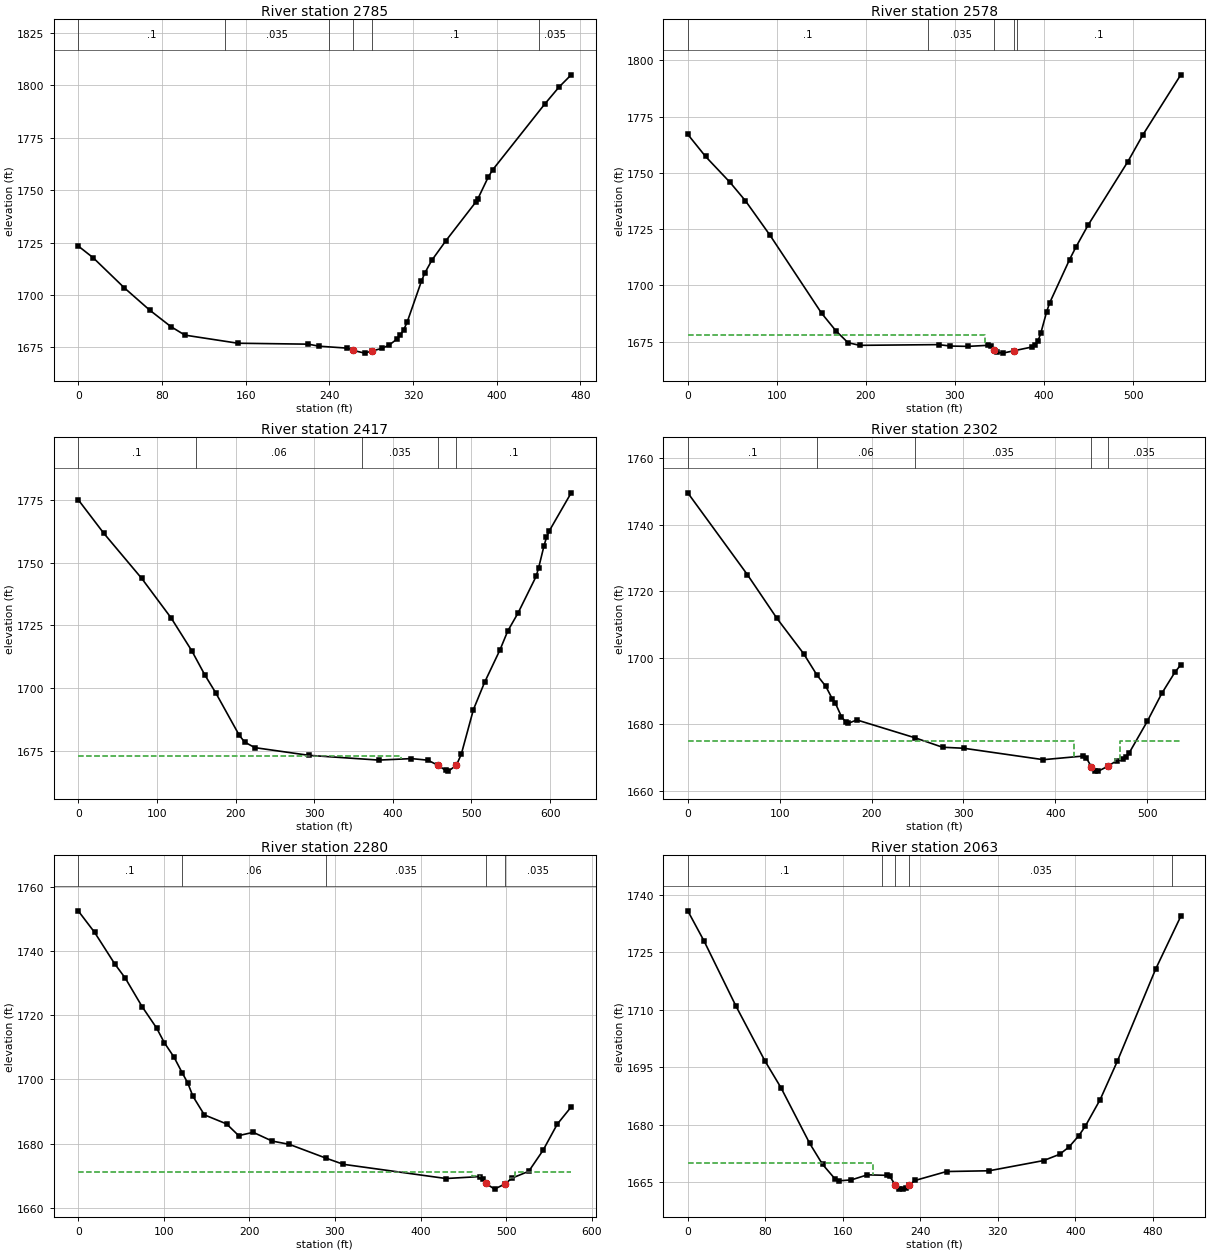
Type RM Length L Ch R = 1 ,2785    ,209.8,206.8,202.3
XS GIS Cut Line= 2
2013606.74056195221213.4694981222013147.99436045221105.659956196
#Sta/Elev= 30
       0 1723.35    14.4  1717.7    44.2 1703.35    68.3 1692.79    88.6 1684.91
     102 1680.86   152.6    1677     220 1676.55   230.1 1675.59   257.1 1674.66
   262.5  1673.6   273.9 1672.28   280.7 1673.29   290.8  1674.6   297.5 1676.23
   304.3 1678.83   307.6 1680.77     311 1683.28   314.4 1687.04     328 1706.49
   331.2 1710.38     338 1716.54   351.4 1725.82   379.9  1744.2   381.8 1745.63
   391.9 1756.17   396.2 1759.68   445.8 1790.92   459.7 1799.16   471.2 1804.92
#Mann= 6 ,-1 , 0
       0      .1       0     140    .035       0     240      .1       0
   262.5    .045       0   280.7      .1       0     440    .035       0
Bank Sta=262.5,280.7
XS Rating Curve= 0 ,0
Exp/Cntr=0.3,0.1

Type RM Length L Ch R = 1 ,2578    ,160.8,161.3,160.3
XS GIS Cut Line= 3
2013733.13445056220993.4534030022013599.52280789 220950.84169294
2013186.18873342 220952.10095244
#Sta/Elev= 30
       0 1767.15      20 1757.31    47.5  1745.8    64.8 1737.61    92.3 1722.35
   150.3 1687.66   166.4 1679.83   179.9 1674.59     193  1673.4   281.6 1673.72
   294.7 1673.09   314.5 1672.94   337.4 1673.41   340.6 1673.29   344.1 1671.37
   347.2 1670.32   353.8 1669.94   366.6 1671.02   386.6 1672.67   389.8 1673.52
   393.1 1675.15   396.4 1678.78     403 1688.31   406.3  1692.2   428.7 1711.48
   435.8 1717.01   449.4 1726.73   494.2 1755.04   511.2 1767.02   553.6  1793.6
#Mann= 5 ,-1 , 0
       0      .1       0  270.24    .035       0   344.1    .045       0
   366.6    .035       0  370.24      .1       0
#XS Ineff= 2 , 0
             334    1678
Permanent Ineff=
       F       F
Bank Sta=344.1,366.6
XS Rating Curve= 0 ,0
Exp/Cntr=0.3,0.1

Type RM Length L Ch R = 1 ,2417    ,111.5,115.1,118
XS GIS Cut Line= 3
2013791.05804579220899.2475139252013649.32948762220786.674768367
2013203.62607364220797.789636138
#Sta/Elev= 30
       0 1775.04    32.4 1761.74    80.8 1743.71   118.2 1727.98   144.4 1714.95
   161.1 1705.28   174.9  1698.2   204.8 1681.32   211.6 1678.64   224.5 1676.42
   293.4 1673.35     382 1671.46   423.7 1672.05   444.4 1671.43   457.3 1669.43
   467.3 1667.32   470.7 1667.07   480.9 1669.44   487.1 1673.83   502.5 1691.57
   516.6 1702.33   536.3 1715.33   546.1 1722.78   559.3 1730.01   582.2 1744.53
   585.5 1748.06   592.2 1756.66   595.4 1760.06   598.6 1762.44   626.8 1777.77
#Mann= 5 ,-1 , 0
       0      .1       0     150     .06       0     361    .035       0
   457.3    .045       0   480.9      .1       0
#XS Ineff= 2 , 0
             410    1673
Permanent Ineff=
       F       F
Bank Sta=457.3,480.9
XS Rating Curve= 0 ,0
Exp/Cntr=0.5,0.3

Type RM Length L Ch R = 1 ,2302    ,22.4,22.5,22.6
XS GIS Cut Line= 3
2013790.08752963220814.1216054562013659.53197411220728.704938769
2013284.53197408220664.816049889
#Sta/Elev= 30
       0 1749.58    64.9 1724.98    97.1 1711.82   126.1 1701.23   140.7 1694.75
   150.2 1691.42   157.2 1687.68   160.6 1686.34   167.2 1682.33   171.8 1680.71
   174.6 1680.29   183.9 1681.33   247.1 1675.97   277.2 1673.12   300.4 1672.81
   386.9 1669.38   430.2 1670.47   433.5 1669.96   439.1 1667.28   443.5 1665.99
   446.8 1665.94   456.8 1667.37   466.8 1669.09   473.4 1669.47   476.7 1670.08
   480.1 1671.33     500 1680.92   515.8 1689.32     530 1695.65   536.4 1697.89
#Mann= 5 ,-1 , 0
       0      .1       0   140.7     .06       0   247.1    .035       0
   439.1    .045       0   456.8    .035       0
#XS Ineff= 4 ,-1
       0     420    1675     420     430    1670     465     470  1669.5
     470  536.42    1675
Permanent Ineff=
       F       F       F       F
Bank Sta=439.1,456.8
XS Rating Curve= 0 ,0
Exp/Cntr(USF)=0,0
Exp/Cntr=0.5,0.3

Type RM Length L Ch R = 1 ,2280    ,216.6,217,217.5
XS GIS Cut Line= 3
2013826.32758749 220806.836069222013710.06708786220716.180560582
2013287.93074993220642.133694749
#Sta/Elev= 30
       0 1752.63    19.2 1745.89    42.6 1736.11      55 1731.63    74.6 1722.76
    91.6 1716.06   100.7 1711.45     112 1706.95   121.5 1702.08     128 1698.92
     134 1694.77   147.4 1688.95   173.3 1686.13   187.5 1682.47   204.5  1683.5
   226.6 1680.77   246.6 1679.75   289.5 1675.44   309.9 1673.51   429.8 1669.08
   469.8  1669.7   473.1 1669.05   476.3 1667.56   486.4 1665.77   499.2 1667.46
   506.4 1669.16   526.4 1671.33   543.1 1677.88   559.7 1686.04     576 1691.43
#Mann= 5 ,-1 , 0
       0      .1       0   121.5     .06       0   289.5    .035       0
   476.3    .045       0   499.2    .035       0
#XS Ineff= 4 ,-1
       0     460    1671     460     470  1669.8     505     510  1669.2
     510  576.01    1671
Permanent Ineff=
       F       F       F       F
Bank Sta=476.3,499.2
XS Rating Curve= 0 ,0
Exp/Cntr(USF)=0,0
Exp/Cntr=0.5,0.3

Type RM Length L Ch R = 1 ,2063    ,87.2,83.3,81.1
XS GIS Cut Line= 2
2013671.69614875220484.9259038932013166.79378722220421.303106796
#Sta/Elev= 30
       0 1735.76    16.8 1727.89    49.9 1710.83    79.6 1696.63    96.2 1689.62
   125.9 1675.07   139.1 1669.62   152.1 1665.79   155.7 1665.31   168.9 1665.56
   185.4 1666.88   205.3 1666.75   208.6 1666.48   214.2 1664.21   218.5 1663.27
   221.8 1663.15   225.1 1663.42   228.4 1664.29     235 1665.44   267.1 1667.74
   311.1 1667.94   367.3  1670.6   383.8 1672.23   393.4 1674.11   403.7  1677.1
   410.3 1679.54   425.7 1686.51   443.4 1696.51     483 1720.57   508.9 1734.33
#Mann= 5 ,-1 , 0
       0      .1       0     200    .035       0   214.2    .045       0
   228.4    .035       0     500      .1       0
#XS Ineff= 2 , 0
           191.3    1670
Permanent Ineff=
       F       F
Bank Sta=214.2,228.4
XS Rating Curve= 0 ,0
Exp/Cntr(USF)=0,0
Exp/Cntr=0.5,0.3

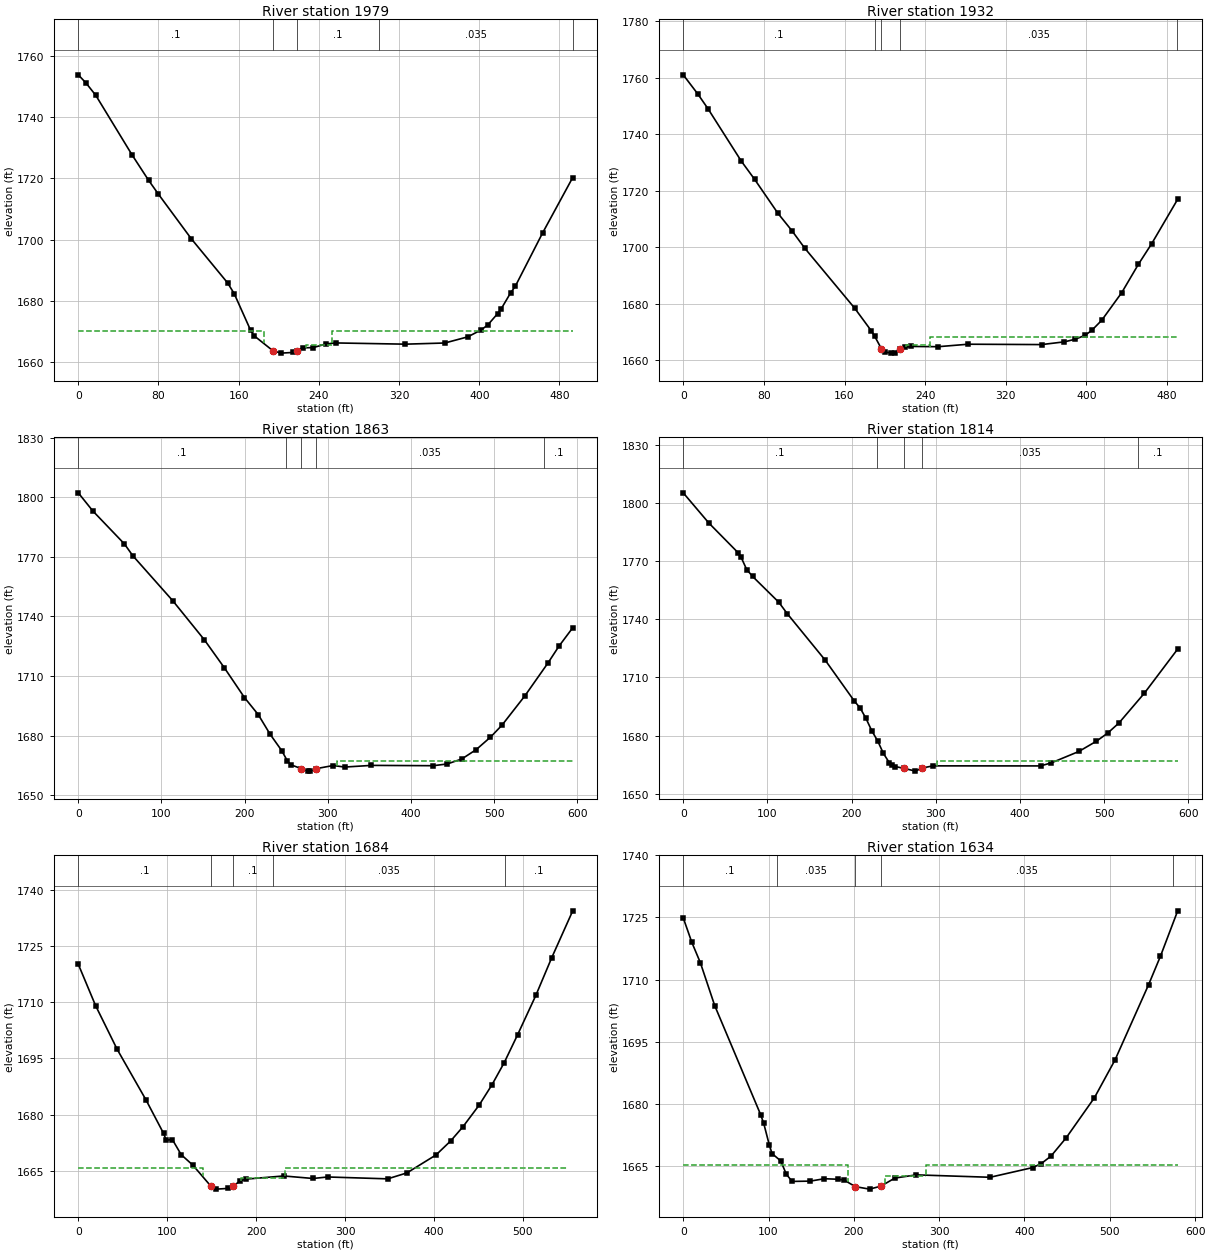
Type RM Length L Ch R = 1 ,1979    ,48.9,47,45.7
XS GIS Cut Line= 2
2013672.56749721 220365.863323732013179.84442736220387.316154018
#Sta/Elev= 30
       0 1753.85     7.7 1751.19    17.5 1747.13    53.7 1727.65    70.1 1719.39
    79.9 1714.85   112.8 1700.22   148.9 1685.84   155.5 1682.33   171.9 1670.32
   175.2 1668.58   194.4 1663.57   202.3 1662.85   214.6 1663.08   217.9 1663.65
   224.4  1664.6   234.3 1664.65   247.4 1665.88   257.2 1666.18   326.2 1665.78
   365.6 1666.16   388.6 1668.18   401.8 1670.43   408.4 1672.04   418.2 1675.73
   421.5 1677.14   431.3 1682.58   435.8 1684.64   463.2 1702.18   493.2 1720.27
#Mann= 5 ,-1 , 0
       0      .1       0   194.4    .045       0   217.9      .1       0
     300    .035       0  493.19      .1       0
#XS Ineff= 3 ,-1
       0     185    1670   227.5     253  1665.4     253  493.19    1670
Permanent Ineff=
       F       F       F
Bank Sta=194.4,217.9
XS Rating Curve= 0 ,0
Exp/Cntr(USF)=0,0
Exp/Cntr=0.5,0.3

Type RM Length L Ch R = 1 ,1932    ,71.1,68.8,66.3
XS GIS Cut Line= 2
2013662.87912224220300.8128060822013176.82801345220366.466606513
#Sta/Elev= 30
       0 1761.09    14.5 1754.28    24.5  1749.1    57.6 1730.49    70.8 1724.04
      94 1711.96   107.7 1705.88   120.5 1699.65   170.1 1678.33   186.7 1670.26
     190 1668.34   196.6 1663.96   199.9 1662.82   206.6 1662.41   209.9 1662.63
   214.8  1663.7   219.8 1664.47   226.4 1664.78   252.9 1664.69   282.7 1665.57
   355.5 1665.44   378.1 1666.41   388.6 1667.31   398.6 1668.72   405.2 1670.45
   415.1 1674.04     435 1683.86   451.5  1693.9   464.8 1701.28   490.5 1716.97
#Mann= 5 ,-1 , 0
       0      .1       0     190    .035       0   196.6    .045       0
   214.8    .035       0     490      .1       0
#XS Ineff= 3 ,-1
       0   190.3    1668   221.1     245  1665.4     245 490.465    1668
Permanent Ineff=
       F       F       F
Bank Sta=196.6,214.8
XS Rating Curve= 0 ,0
Exp/Cntr(USF)=0,0
Exp/Cntr=0.5,0.3

Type RM Length L Ch R = 1 ,1863    ,49.8,49,48.8
XS GIS Cut Line= 2
2013707.86242959220178.1075961362013140.71436341220356.830974525
#Sta/Elev= 30
       0 1802.25    17.5 1793.12    55.4 1776.55    65.7 1770.52   113.9 1747.77
   151.7 1728.18   175.8 1714.05   199.9  1699.1   216.5 1690.49   230.8 1680.57
   244.6 1672.44   251.5 1667.19   255.7 1665.26   268.4  1663.3   276.6 1662.07
     279 1662.08   285.9 1663.29   306.5  1664.9   320.3 1664.12   352.5 1664.96
   426.9  1664.8   443.8 1665.69   461.3 1668.21   478.5  1672.9   495.7 1679.18
   509.5  1685.2     537 1699.95   564.8 1716.52   578.2  1725.1   594.6 1734.28
#Mann= 5 ,-1 , 0
       0      .1       0     250    .035       0   268.4    .045       0
   285.9    .035       0     560      .1       0
#XS Ineff= 2 , 0
                             311            1667
Permanent Ineff=
       F       F
Bank Sta=268.4,285.9
XS Rating Curve= 0 ,0
Exp/Cntr=0.3,0.1

Type RM Length L Ch R = 1 ,1814    ,149.3,130.4,105.2
XS GIS Cut Line= 2
2013693.84919685220127.1748576822013136.14472247220311.753206852
#Sta/Elev= 30
       0  1805.4    30.5 1789.77    65.1  1774.5    68.5 1772.34    75.4 1765.77
    82.4 1762.21   113.5 1748.89   123.8 1742.85   168.7 1718.93   203.3 1697.82
   210.2 1694.22   217.1 1688.88     224 1682.47     231 1677.23   237.9 1670.71
   244.8 1665.99   248.2 1664.61   251.7 1663.98   262.3 1663.04   275.9  1661.6
   283.8 1663.18   296.6 1664.32   424.5 1664.29   437.3 1665.86     470 1671.75
   490.8 1677.02   504.4 1681.27   517.8 1686.52   547.9 1701.86   587.5 1724.68
#Mann= 5 ,-1 , 0
       0      .1       0     230    .035       0   262.3    .045       0
   283.8    .035       0     540      .1       0
#XS Ineff= 1 ,-1
     302587.4551    1667
Permanent Ineff=
       F
Bank Sta=262.3,283.8
XS Rating Curve= 0 ,0
Exp/Cntr(USF)=0,0
Exp/Cntr=0.5,0.3

Type RM Length L Ch R = 1 ,1684    ,52.2,49.5,53.3
XS GIS Cut Line= 4
2013485.05769285219988.5676999392013394.81048002220028.926701953
2013406.02131391220149.4431662982013094.92067339220276.686130979
#Sta/Elev= 30
       0 1720.14    19.5 1709.09    43.7 1697.46    76.2 1683.94    95.9 1675.04
    98.9 1673.25   105.9 1673.36   115.7 1669.37   128.9 1666.55   148.7 1661.08
   155.3 1660.17   168.5 1660.36   174.5 1661.01   181.6  1662.3   188.2 1662.83
   230.9 1663.68   263.9 1663.01   280.5 1663.41   347.9 1662.91   369.6  1664.5
   402.3 1669.29   418.8 1673.03   432.5 1676.78   450.7 1682.54   465.2 1687.99
     479 1693.91   494.1 1701.37   514.5 1711.81   532.2 1721.77     556 1734.37
#Mann= 5 ,-1 , 0
       0      .1       0   148.7    .045       0   174.5      .1       0
  218.86    .035       0   479.9      .1       0
#XS Ineff= 3 ,-1
       0   139.7  1665.8   183.5     232  1663.2     232   549.9  1665.8
Permanent Ineff=
       F       F       F
Bank Sta=148.7,174.5
XS Rating Curve= 0 ,0
Exp/Cntr(USF)=0,0
Exp/Cntr=0.5,0.3

Type RM Length L Ch R = 1 ,1634    ,91.6,108.8,123.7
XS GIS Cut Line= 4
2013481.13390099219959.4195318192013346.30803147219989.155324658
2013366.54169853220134.0688942312013095.48121509220250.901213026
#Sta/Elev= 30
       0 1724.89    10.1 1718.96    20.1 1714.05    36.9 1703.71    90.7 1677.42
    94.4 1675.26   100.8 1670.16   104.1    1668   114.2 1666.25   120.9 1663.01
   127.6 1661.28   148.8 1661.35   165.4 1661.93   181.9  1661.8   188.6  1661.6
   201.8 1660.02   218.4 1659.42   231.6 1660.13   248.2  1662.1   273.4 1662.86
   359.7 1662.28   409.6 1664.62   419.6 1665.57   431.1 1667.39     449 1671.83
     482 1681.48   506.1 1690.58   545.4 1708.71   559.4 1715.63   579.6 1726.58
#Mann= 5 ,-1 , 0
       0      .1       0     110    .035       0   201.8    .045       0
   231.6    .035       0  574.39      .1       0
#XS Ineff= 3 ,-1
       0   192.6  1665.2   236.9   284.4  1662.5   284.4  579.55  1665.2
Permanent Ineff=
       F       F       F
Bank Sta=201.8,231.6
XS Rating Curve= 0 ,0
Exp/Cntr(USF)=0,0
Exp/Cntr=0.5,0.3

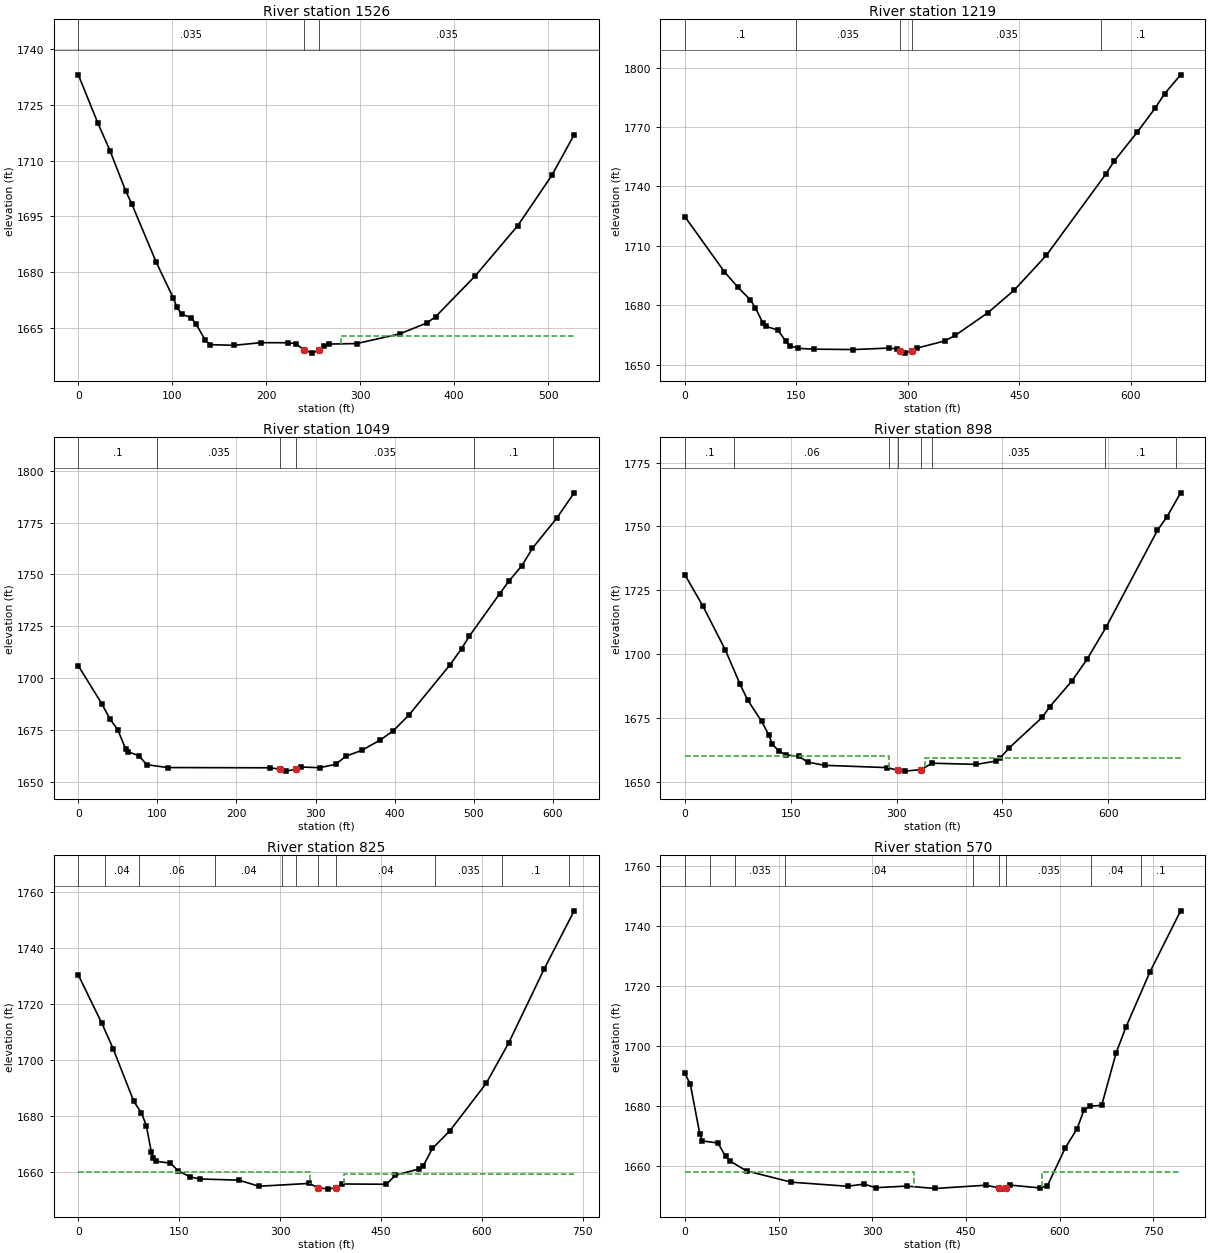
Type RM Length L Ch R = 1 ,1526    ,298.1,306.9,313.7
XS GIS Cut Line= 3
2013465.56560512219867.7244451692013375.60212327219880.027143542
2013091.10222339 220211.43108097
#Sta/Elev= 30
       0 1733.06    20.7 1720.14    33.9 1712.54    50.5 1701.79    57.1 1698.23
      83 1682.63   100.9 1673.17     105 1670.54   110.1 1668.75   120.2 1667.76
   125.2  1666.1   135.3 1661.68   140.4 1660.56   165.5 1660.36     194 1661.08
   222.7 1661.06   231.2 1660.84     240 1659.18   248.7 1658.27   256.2 1659.05
   261.4 1660.27   266.2  1660.7   296.2 1660.84   341.8 1663.43   370.8 1666.37
   380.1 1668.04   422.4 1679.03   467.7 1692.56   503.8 1706.03   527.6 1716.96
#Mann= 3 ,-1 , 0
       0    .035       0     240    .045       0   256.2    .035       0
#XS Ineff= 2 , 0
                             280            1663
Permanent Ineff=
       F       F
Bank Sta=240,256.2
XS Rating Curve= 0 ,0
Exp/Cntr(USF)=0,0
Exp/Cntr=0.3,0.1

Type RM Length L Ch R = 1 ,1219    ,167.9,169.5,170.7
XS GIS Cut Line= 2
2013418.67763366219675.0822620672012775.15830786219850.888284964
#Sta/Elev= 30
       0  1724.8    53.2 1696.92    71.3 1689.12    88.3 1682.68    95.1 1678.57
   105.3 1670.79   109.3 1669.28   125.4 1667.43   135.9 1661.68   141.4 1659.61
   152.1 1658.19   173.3 1657.78   226.9 1657.57   275.3 1658.34   285.4 1657.83
     290 1656.82   295.7 1655.77     306 1656.91   312.8 1658.34   349.8 1661.94
   363.8  1664.7     408 1676.24   443.3 1687.65   486.6 1705.27   566.1 1746.06
     578 1752.94   608.9 1767.52   632.5 1779.43   645.7 1786.95   667.1 1796.42
#Mann= 5 ,-1 , 0
       0      .1       0     150    .035       0     290    .045       0
     306    .035       0     560      .1       0
Bank Sta=290,306
XS Rating Curve= 0 ,0
Exp/Cntr=0.3,0.1

Type RM Length L Ch R = 1 ,1049    ,157,151.2,144.1
XS GIS Cut Line= 2
2013372.93775224219546.2639726982012753.18932169 219641.60988509
#Sta/Elev= 30
       0 1706.04    29.9 1687.59    39.9 1680.47    49.8 1675.28    59.8 1665.99
    63.1 1664.55    76.4 1662.81    86.4 1658.41   112.9 1657.03   242.4 1656.91
   255.6 1656.24   262.3 1655.31   275.6 1656.23   282.2 1657.29   305.4 1656.96
   325.4 1658.61   338.6 1662.54   358.6 1665.33   381.8 1670.31   398.4 1674.79
   418.3 1682.43   469.7 1706.35   484.7 1714.34   494.6  1720.4   532.6 1740.62
   544.4 1746.75     561  1754.3   574.3 1762.68   604.9 1777.08     627 1789.32
#Mann= 6 ,-1 , 0
       0      .1       0     100    .035       0   255.6    .045       0
   275.6    .035       0     500      .1       0     600    .035       0
Bank Sta=255.6,275.6
XS Rating Curve= 0 ,0
Exp/Cntr(USF)=0,0
Exp/Cntr=0.5,0.3

Type RM Length L Ch R = 1 ,898     ,71.5,73.4,75.6
XS GIS Cut Line= 5
2013439.83367464219413.2410465372013323.72695875219370.181602231
2013291.43237552219403.245104109 2013049.2230013 219485.51939948
2012776.25688114219530.885599731
#Sta/Elev= 30
       0  1731.1    25.9 1718.67    57.4 1701.64    78.4 1688.16    88.9 1682.08
   108.8 1673.69     119  1668.4   123.8 1664.73   133.3 1662.13   142.7 1660.52
   161.5    1660   174.1  1657.7   198.4 1656.44   286.5 1655.55     302 1654.51
   312.3 1654.17   334.5 1654.78   350.8 1657.27   413.2 1656.81   440.4  1658.1
     447 1659.34   460.1 1663.38   506.8 1675.31   516.8 1679.26   548.8 1689.57
     570 1697.96   597.3 1710.68   669.8 1748.47   683.1 1753.68   702.6 1763.14
#Mann= 8 ,-1 , 0
       0      .1       0      70     .06       0  290.05     .04       0
     302    .045       0   334.5     .04       0  350.05    .035       0
  595.85      .1       0  695.85    .035       0
#XS Ineff= 2 , 0
             290  1659.9   340.2          1659.2
Permanent Ineff=
       F       F
Bank Sta=302,334.5
XS Rating Curve= 0 ,0
Exp/Cntr(USF)=0,0
Exp/Cntr=0.5,0.3

Type RM Length L Ch R = 1 ,825     ,260.6,254.8,248.6
XS GIS Cut Line= 5
2013453.67421032219374.7951141212013289.12561957219295.596493344
2013252.21752445219344.0383681882012988.47842808219427.850500856
2012774.71904384219464.758595975
#Sta/Elev= 30
       0 1730.34      35 1713.05    51.9 1703.88    82.4 1685.18    93.7 1681.04
   101.1 1676.47   108.4 1667.17   111.5 1664.89   115.1 1663.72     137 1663.04
   147.9 1660.38   166.1 1658.14   180.7 1657.38   238.9 1656.96   268.4 1654.78
     343 1655.79   356.1 1654.33   371.8 1653.75     383 1654.33   392.7 1655.59
     458 1655.49   471.5 1658.71   505.9 1660.94   512.7 1662.03   526.4 1668.29
     552 1674.49   606.3 1691.56   639.6 1705.94   692.8  1732.6   737.2 1753.31
#Mann= 11 ,-1 , 0
       0      .1       0      40     .04       0      90     .06       0
  202.62     .04       0  303.52     .06       0  323.52     .04       0
   356.1    .045       0     383     .04       0  530.25    .035       0
  630.25      .1       0  730.25    .035       0
#XS Ineff= 2 , 0
           344.5  1659.9   394.5          1659.2
Permanent Ineff=
       F       F
Bank Sta=356.1,383
XS Rating Curve= 0 ,0
Exp/Cntr(USF)=0,0
Exp/Cntr=0.5,0.3

Type RM Length L Ch R = 1 ,570     ,196.4,196.6,196.5
XS GIS Cut Line= 3
2013413.47210568219296.5742540942013089.76684755219116.210620536
  2012730.938145219340.241239061
#Sta/Elev= 30
       0 1690.96     8.9 1687.27    23.9  1670.9    27.7 1668.48    53.1  1667.8
    65.2 1663.32    72.4 1661.78    98.8 1658.52   170.4 1654.77   260.5 1653.41
   286.8 1654.13   305.6 1652.93   354.9 1653.48   400.4 1652.67   481.6 1653.76
   502.6 1652.89   506.3 1652.46   513.5 1652.77   520.6  1653.8   568.3 1652.86
   580.2 1653.51   609.2 1666.25   627.8 1672.48   638.9 1678.74   649.2 1680.06
   667.2 1680.29   690.4 1697.74   705.9 1706.23   744.6 1724.68   793.6 1744.94
#Mann= 9 ,-1 , 0
       0     .04       0      40     .06       0      80    .035       0
     160     .04       0  460.56    .035       0   502.6    .045       0
   513.5    .035       0  650.56     .04       0  730.56      .1       0
#XS Ineff= 2 , 0
           366.5    1658   572.5            1658
Permanent Ineff=
       F       F
Bank Sta=502.6,513.5
XS Rating Curve= 0 ,0
Exp/Cntr(USF)=0,0
Exp/Cntr=0.3,0.1

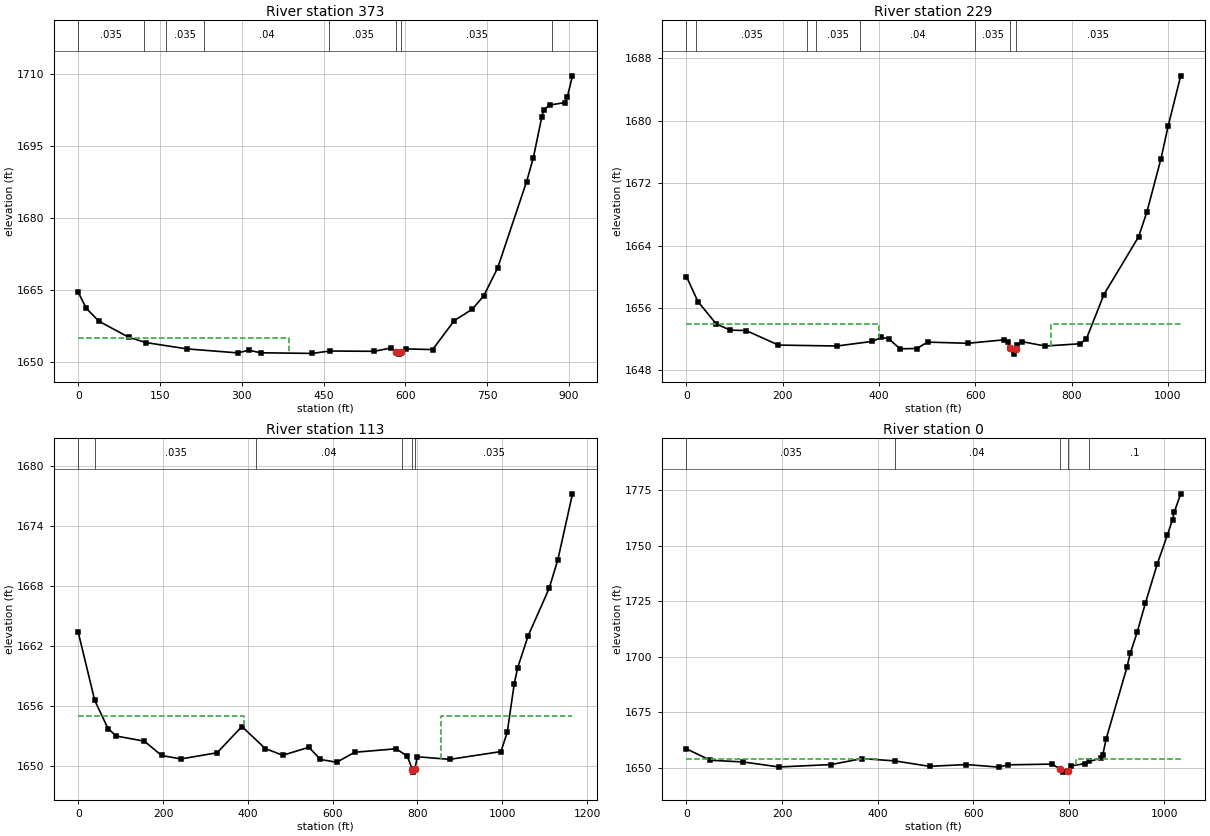
Type RM Length L Ch R = 1 ,373     ,141.7,144.7,146.4
XS GIS Cut Line= 3
2013375.64906985219245.1805213842012942.05531985218978.253438056
2012604.81573647219187.888854697
#Sta/Elev= 30
       0 1664.49    14.8 1661.15    37.8 1658.47    92.6 1655.12   123.6 1654.02
   199.7 1652.69   292.2 1651.86   312.8 1652.41   334.6 1651.88   428.8 1651.75
   461.7 1652.25   542.7 1652.19   573.6 1652.88   582.51652.132   587.9  1651.6
   592.7 1652.07   600.7 1652.69   649.8 1652.55   689.5 1658.59   722.8    1661
   743.6 1663.78     769 1669.57   822.2 1687.63   834.6 1692.63     850 1701.11
   853.3 1702.49   864.2 1703.59   892.8 1704.11   896.8 1705.26   906.3 1709.69
#Mann= 8 ,-1 , 0
       0    .035       0     120     .04       0     160    .035       0
     230     .04       0     460    .035       0   582.5    .045       0
   592.7    .035       0  869.17     .04       0
#XS Ineff= 2 , 0
             386    1655
Permanent Ineff=
       F       F
Bank Sta=582.5,592.7
XS Rating Curve= 0 ,0
Exp/Cntr(USF)=0,0
Exp/Cntr=0.3,0.1

Type RM Length L Ch R = 1 ,229     ,114.6,115.7,115.5
XS GIS Cut Line= 4
2013389.97198647219202.2117713842012860.02406985218876.690938041
2012729.81573647218923.5659380412012531.89906982219101.951354697
#Sta/Elev= 30
       0 1660.02    23.9 1656.81      62 1653.94    90.9 1653.16     124  1653.1
   191.1 1651.24   312.6 1651.12   385.8 1651.71   405.1 1652.24   420.5 1652.02
   443.9 1650.76   478.2  1650.8   501.3 1651.62   584.6 1651.47   659.2 1651.91
   667.5 1651.68   672.9 1650.86   680.1 1650.08   683.8 1650.76   687.1 1651.31
   696.3 1651.69     745 1651.12   818.5 1651.41     831 1652.06   867.3 1657.72
   939.3 1665.12   956.5 1668.29   985.9 1675.14  1000.6 1679.28  1026.8 1685.75
#Mann= 8 ,-1 , 0
       0     .04       0      20    .035       0     250     .04       0
     270    .035       0     360     .04       0     600    .035       0
   672.9    .045       0   683.8    .035       0
#XS Ineff= 2 , 0
             401    1654   757.5            1654
Permanent Ineff=
       F       F
Bank Sta=672.9,683.8
XS Rating Curve= 0 ,0
Exp/Cntr(USF)=0,0
Exp/Cntr=0.3,0.1

Type RM Length L Ch R = 1 ,113     ,112.8,112.8,112.8
XS GIS Cut Line= 4
2013435.54490316219183.982604697 2012795.2554957218788.574791998
2012720.39383113218808.1199651662012517.57615316219075.909688041
#Sta/Elev= 30
       0 1663.36    38.9 1656.53    70.2 1653.72    89.5 1652.97     156 1652.45
   196.5 1651.02   241.8 1650.67   327.6 1651.29     386 1653.92   441.2 1651.71
   482.4 1651.04   544.1 1651.84   571.1 1650.62   609.6 1650.34     652 1651.34
   749.6 1651.69   776.1 1650.95   788.1 1649.61   789.6 1649.35   793.9 1649.66
   799.8 1650.89   876.1 1650.63     997 1651.41  1011.9 1653.34  1028.4  1658.2
  1036.6 1659.83  1061.3 1663.02  1110.7 1667.76  1131.3 1670.64  1165.8 1677.24
#Mann= 6 ,-1 , 0
       0     .04       0      40    .035       0     420     .04       0
  762.54    .035       0   788.1    .045       0   793.9    .035       0
#XS Ineff= 2 , 0
             390    1655   855.5            1655
Permanent Ineff=
       F       F
Bank Sta=788.1,793.9
XS Rating Curve= 0 ,0
Exp/Cntr(USF)=0,0
Exp/Cntr=0.3,0.1

Type RM Length L Ch R = 1 ,0       ,56.2,55.8,58.6
XS GIS Cut Line= 4
 2013453.7506674219136.7546449972012846.24741375218795.353991515
2012753.86838492218601.9558677252012799.92689779218487.862290824
#Sta/Elev= 30
       0 1658.57    49.6 1653.45   119.1 1652.66   193.8 1650.41   302.6 1651.49
   367.5 1654.19   435.7 1653.15   508.6 1650.69   585.8 1651.51   653.5 1650.33
   672.3 1651.37   765.5  1651.7     781 1649.52   787.3 1648.09   799.11648.796
   805.5 1650.97   834.6  1651.9   842.9 1652.91   867.3 1654.34     871 1655.69
   878.2 1663.05   921.6 1695.19   928.6 1701.55     943 1710.99   960.5  1724.3
   985.3 1741.88  1006.5 1754.89  1017.1  1761.8  1020.6  1765.1  1034.2 1773.36
#Mann= 5 ,-1 , 0
       0    .035       0   435.7     .04       0     781    .045       0
   799.1     .04       0   842.9      .1       0
#XS Ineff= 2 , 0
             400    1654     815            1654
Permanent Ineff=
       F       F
Bank Sta=781,799.1
XS Rating Curve= 0 ,0
Exp/Cntr(USF)=0,0
Exp/Cntr=0.5,0.3
LCMann Table=0

Chan Stop Cuts=-1
Use User Specified Reach Order=0
Composite Channel Slope=5